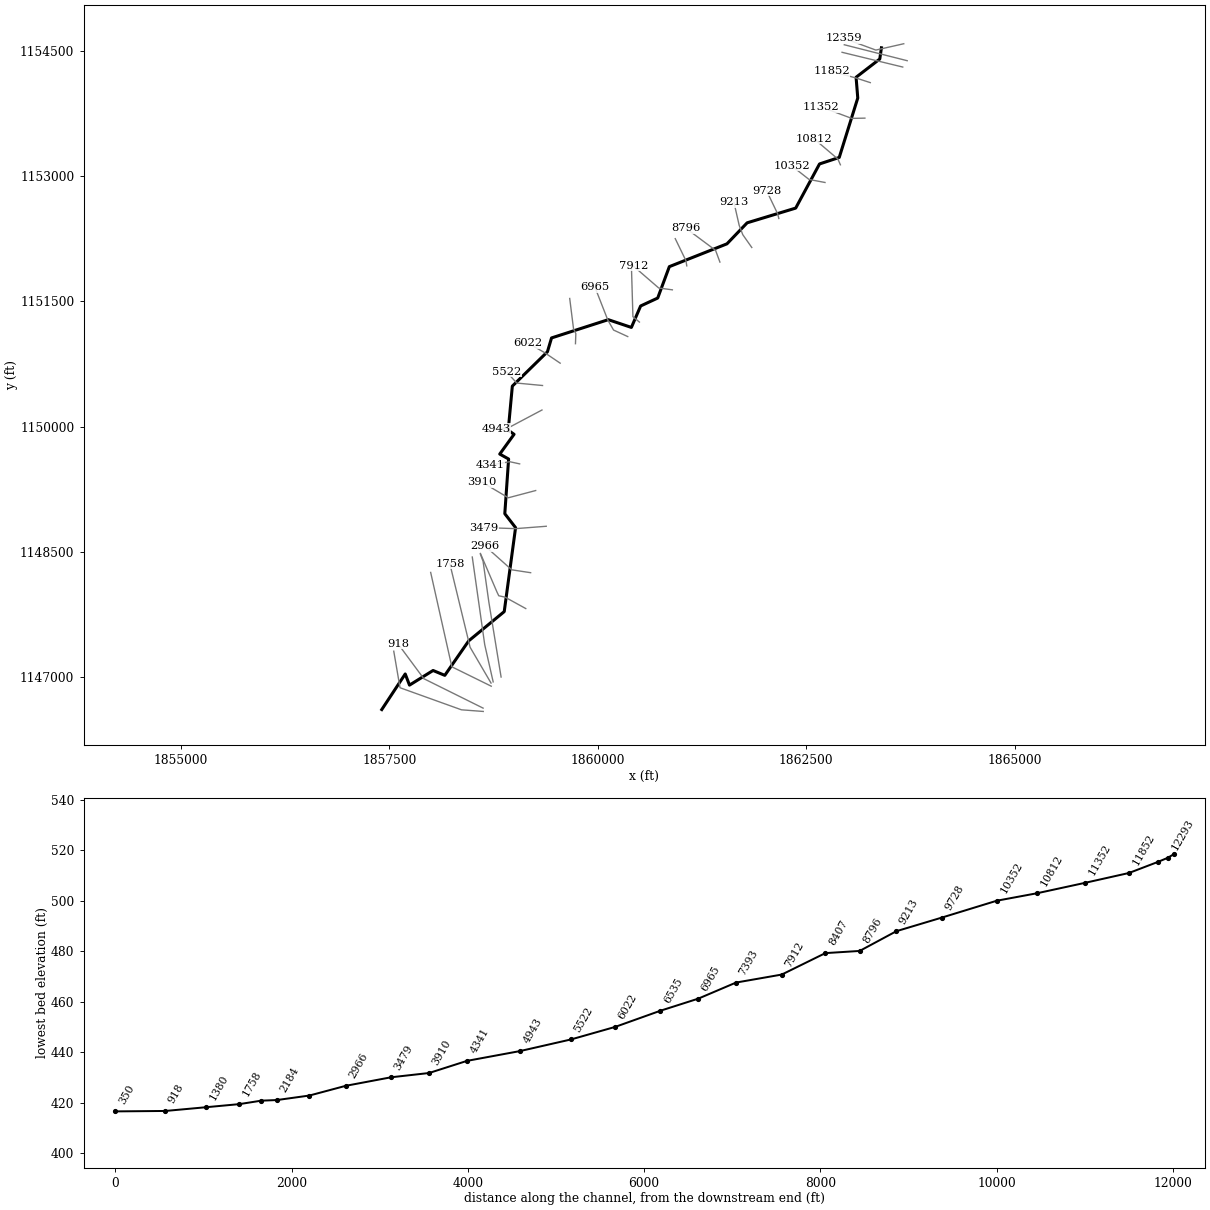
--- Mud Creek.prj (project) ---

Proj Title=Mud Creek Limited Detail Study
Current Plan=p01
Default Exp/Contr=0.3,0.1
English Units
Geom File=g01
Flow File=f01
Plan File=p01
Y Axis Title=Elevation
X Axis Title(PF)=Main Channel Distance
X Axis Title(XS)=Station
BEGIN DESCRIPTION:
Mud Creek
END DESCRIPTION:
DSS Export Rating Curves= 0
DSS Export Rating Curve Sorted= 0
DSS Export Volume Flow Curves= 0
DXF OffsetX= 0
DXF OffsetY= 0
DXF ScaleX= 1
DXF ScaleY= 10

--- Mud Creek.p01 (plan) ---

Plan Title=100 Yr Single
Program Version=3.12
Short Identifier=100 Yr Singl
Geom File=g01
Flow File=f01
Subcritical Flow
K Sum by GR= 0
Std Step Tol= 0.01
Critical Tol= 0.01
Num of Std Step Trials= 20
Max Error Tol= 0.3
Flow Tol Ratio= 0.001
Split Flow NTrial= 30
Split Flow Tol= 0.02
Split Flow Ratio= 0.02
Log Output Level= 0
Friction Slope Method= 1
Unsteady Friction Slope Method= 2
Unsteady Bridges Friction Slope Method= 1
Parabolic Critical Depth
Global Vel Dist= 0 , 0 , 0
Global Log Level= 0
CheckData=True
Encroach Param=-1 ,0,0, 0
Computation Interval=1HOUR
Output Interval=1HOUR
Run HTab= 0
Run UNet= 0
Run PostProcess= 0
UNET Theta= 1
UNET Theta Warmup= 1
UNET ZTol= 0.02
UNET ZSATol= 0.05
UNET MxIter= 20
UNET MaxInSteps= 0
UNET DtIC= 0
UNET DtMin= 0
UNET MaxCRTS= 20
UNET WFStab= 2
UNET SFStab= 1
UNET WFX= 1
UNET SFX= 1
UNET DSS MLevel= 4
UNET DZMax Abort= 100
UNET Convert EG Bridges=-1
UNET Use Existing IB Tables=-1
UNET Froude Reduction=False
UNET Froude Limit= 1
UNET Froude Power= 10
Instantaneous Interval=1HOUR
Write IC File= 0
Echo Input=False
Echo Output=False
Write Detailed= 0
Detailed Automatic Start=False, 10

--- Mud Creek.f01 (steady flow) ---

Flow Title=100 Yr Single
Number of Profiles=1
Profile Names=100-year
River Rch & RM= Mud Creek,Reach-1,12359
    1153
River Rch & RM= Mud Creek,Reach-1,4341
    1358
Boundary for River Rch & Prof#=Mud Creek,Reach-1,1
Up Type=0
Dn Type=3
Dn Slope=0.0032

--- Mud Creek.g01 (geometry) ---

Geom Title=Existing Conditions

River Reach=Mud Creek,Reach-1
Reach XY= 30
      1863401.42      1154539.61      1863381.63      1154405.00
      1863097.56      1154186.11      1863117.69      1153937.35
      1862895.56      1153225.03      1862659.05      1153147.13
      1862373.44      1152618.00      1861791.29      1152441.59
      1861549.23      1152189.64      1860858.41      1151916.29
      1860718.87      1151540.00      1860514.09      1151444.88
      1860403.20      1151187.73      1860125.99      1151280.82
      1859445.89      1151061.92      1859396.71      1150896.08
      1858975.82      1150484.33      1858926.63      1149955.92
      1858996.40      1149906.74      1858824.84      1149669.99
      1858931.21      1149610.52      1858885.46      1148955.15
      1859014.62      1148788.17      1858878.60      1147781.68
      1858453.13      1147431.70      1858166.05      1147017.66
      1858025.37      1147075.99      1857742.71      1146900.59
      1857691.50      1147034.49      1857410.14      1146607.63

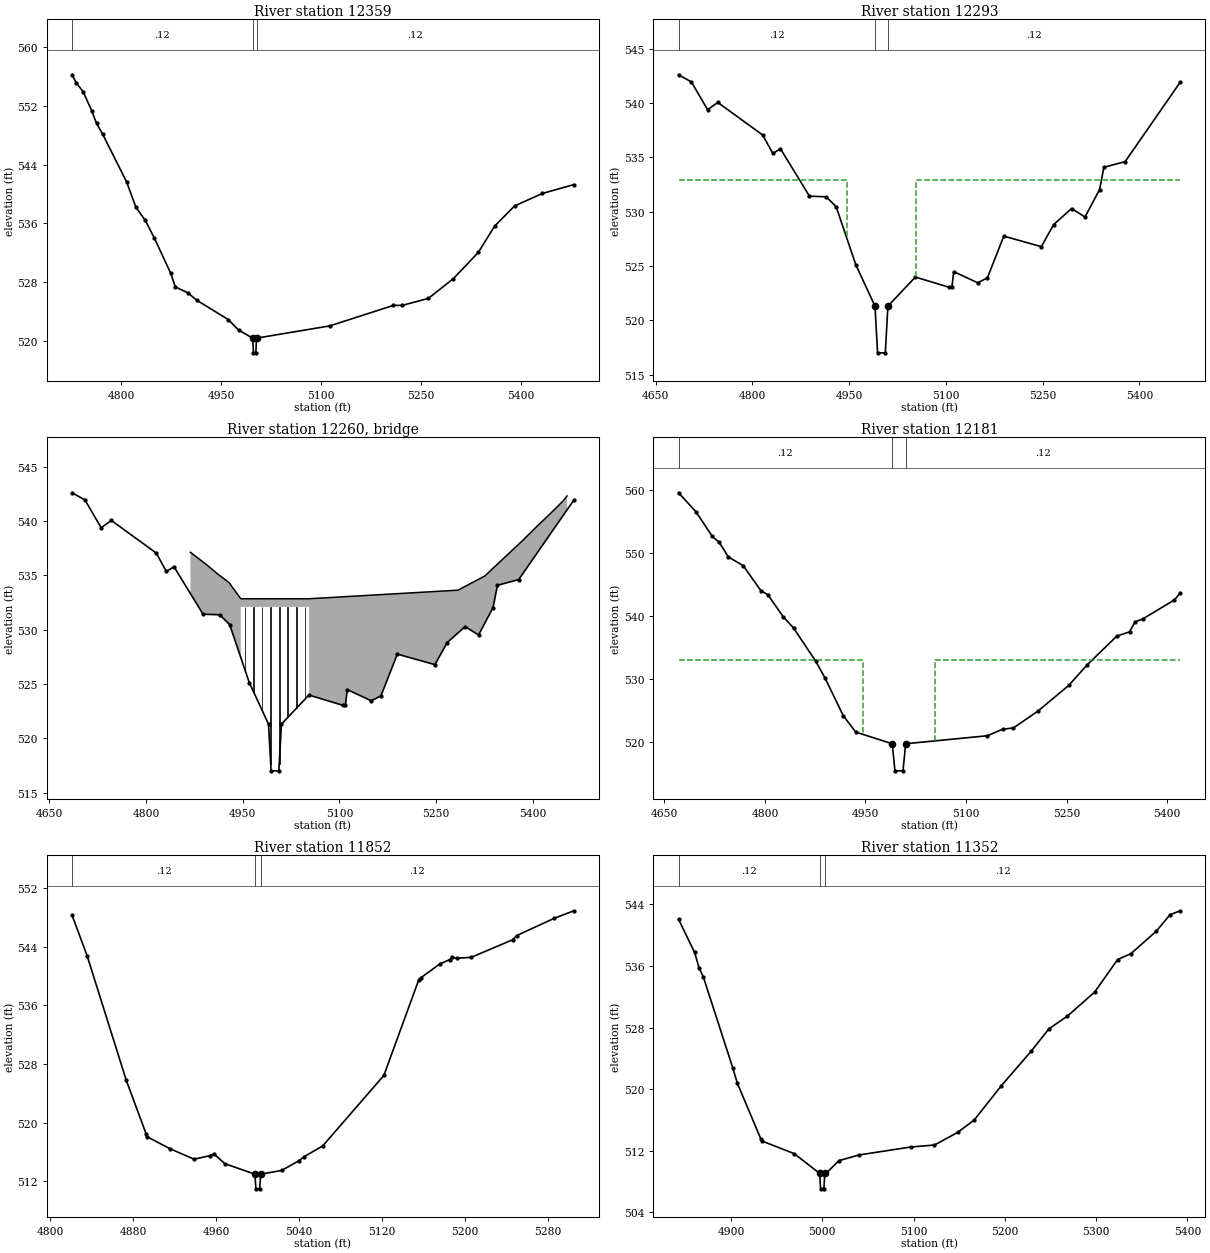
Type RM Length L Ch R = 1,12359,66,66,66
BEGIN DESCRIPTION:
Mud Creek 30
END DESCRIPTION:
XS GIS Cut Line= 3
      1863669.28      1154588.05      1863334.30      1154512.01
      1862949.99      1154653.81
#Sta/Elev= 30
  4726.0  556.24  4732.4  555.12  4742.5  553.95  4755.5  551.35  4762.7  549.63
  4772.1  548.12  4807.9  541.65  4821.9  538.19  4835.9  536.42  4849.7  533.97
  4874.1  529.22  4880.9  527.37  4899.9  526.55  4912.8  525.57  4960.6  522.91
  4976.2  521.47  4997.2  520.39  4998.2  518.39  5001.8  518.39  5002.8  520.39
  5112.9  522.06  5208.3  524.85  5221.5  524.85  5260.8  525.80  5298.4  528.50
  5335.6  532.05  5360.2  535.64  5390.2  538.39  5432.0  540.09  5479.1  541.29
#Mann=3,-1,0
  4726.0    0.12       0  4997.2   0.046       0  5002.8    0.12       0
Bank Sta=4997.2,5002.8
XS Rating Curve= 0
Exp/Cntr=0.5,0.3

Type RM Length L Ch R = 1,12293,112,112,112
BEGIN DESCRIPTION:
Mud Creek 27.0
END DESCRIPTION:
XS GIS Cut Line= 2
      1863710.38      1154384.59      1862956.16      1154575.72
#Sta/Elev= 30
  4685.4  542.61  4705.4  541.95  4730.5  539.39  4746.3  540.06  4815.9  537.06
  4831.6  535.36  4843.4  535.80  4888.4  531.43  4914.3  531.37  4929.7  530.47
  4960.2  525.12  4990.0  521.30  4994.0  517.00  5006.0  517.00  5010.0  521.30
  5052.6  523.98  5105.5  523.03  5109.3  523.07  5112.1  524.48  5149.3  523.45
  5164.3  523.91  5189.7  527.75  5248.0  526.78  5266.8  528.80  5294.8  530.29
  5315.6  529.51  5338.2  532.04  5344.9  534.09  5377.8  534.61  5463.4  541.94
#Mann=3,-1,0
  4685.4    0.12       0  4990.0   0.046       0  5010.0    0.12       0
#XS Ineff=2,0
    0.00 4946.00  532.88 5054.00    0.00  532.88
Bank Sta=4990,5010
XS Rating Curve= 0
Exp/Cntr=0.5,0.3

Type RM Length L Ch R =3,12260,,,
Node Photo=N:\SC_flood\60433\Survey\LDS\all_photos\LDS_MUD_CRK-02.jpg
BEGIN DESCRIPTION:
Mud Creek 26.0
Structure ID: LDS_MUD_CRK_02
Approximate Survey Structure
END DESCRIPTION:
Bridge Culvert--1,0,-1,-1,0
Deck Dist Width WeirC Skew NumUp NumDn MinLoCord MaxHiCord MaxSubmerge Is_Ogee
16.5,33,3,,15,15,,,,0,1,1,,,
  4868.9  4894.1  4911.0  4928.9  4947.0  4947.0  5053.0  5053.0  5283.6  5325.2
  5382.5  5408.4  5423.1  5446.7  5452.9
  537.13  535.98  535.14  534.33  532.85  532.85  532.85  532.85  533.64  534.94
  538.13  539.65  540.47  541.86  542.32
  497.00  497.00  497.00  497.00  497.00  532.10  532.10  497.00  497.00  497.00
  497.00  497.00  497.00  497.00  497.00
  4868.9  4894.1  4911.0  4928.9  4947.0  4947.0  5053.0  5053.0  5283.6  5325.2
  5382.5  5408.4  5423.1  5446.7  5452.9
  537.13  535.98  535.14  534.33  532.85  532.85  532.85  532.85  533.64  534.94
  538.13  539.65  540.47  541.86  542.32
  497.00  497.00  497.00  497.00  497.00  532.10  532.10  497.00  497.00  497.00
  497.00  497.00  497.00  497.00  497.00
Pier Skew, UpSta & Num, DnSta & Num=,4953.6,2,4953.6,2,0,0,0,0,0
       1       1
  526.39  532.10
       1       1
  520.31  532.10
Pier Skew, UpSta & Num, DnSta & Num=,4966.9,2,4966.9,2,0,0,0,0,0
       1       1
  524.44  532.10
       1       1
  518.11  532.10
Pier Skew, UpSta & Num, DnSta & Num=,4980.1,2,4980.1,2,0,0,0,0,0
       1       1
  522.65  532.10
       1       1
  516.84  532.10
Pier Skew, UpSta & Num, DnSta & Num=,4993.4,2,4993.4,2,0,0,0,0,0
       1       1
  517.65  532.10
       1       1
  517.40  532.10
Pier Skew, UpSta & Num, DnSta & Num=,5006.6,2,5006.6,2,0,0,0,0,0
       1       1
  517.65  532.10
       1       1
  517.40  532.10
Pier Skew, UpSta & Num, DnSta & Num=,5019.9,2,5019.9,2,0,0,0,0,0
       1       1
  521.92  532.10
       1       1
  518.82  532.10
Pier Skew, UpSta & Num, DnSta & Num=,5033.1,2,5033.1,2,0,0,0,0,0
       1       1
  522.75  532.10
       1       1
  519.57  532.10
Pier Skew, UpSta & Num, DnSta & Num=,5046.4,2,5046.4,2,0,0,0,0,0
       1       1
  523.59  532.10
       1       1
  519.75  532.10
Abutment Skew #Up #Dn=,2,2
  4947.0  4948.0
  532.10  527.47
  4947.0  4948.0
  532.10  521.07
Abutment Skew #Up #Dn=,2,2
  5052.0  5053.0
  523.94  532.10
  5052.0  5053.0
  519.83  532.10
BR Coef=1,1,0,1.25,0,,,0.8,0,2,0,
WSPro=,,,, 1 ,,,, 0 ,,,, 0 ,,,,-1 ,-1 ,-1 , 0 , 0 , 0 , 0 , 0
BC Design=,,0,,0,,,,,,

Type RM Length L Ch R = 1,12181,329,329,329
BEGIN DESCRIPTION:
Mud Creek 25.0
END DESCRIPTION:
XS GIS Cut Line= 2
      1863656.95      1154308.55      1862929.44      1154485.29
#Sta/Elev= 30
  4671.1  559.50  4697.0  556.50  4721.5  552.57  4731.9  551.61  4745.5  549.31
  4767.6  547.94  4794.1  543.94  4804.1  543.35  4827.5  539.80  4842.7  538.04
  4875.9  532.75  4889.9  530.05  4916.8  524.15  4935.5  521.52  4990.0  519.67
  4994.0  515.37  5006.0  515.37  5010.0  519.67  5132.0  520.94  5154.7  521.98
  5170.8  522.18  5207.7  524.88  5253.2  528.92  5281.0  532.21  5324.9  536.74
  5344.1  537.43  5352.0  539.00  5364.4  539.52  5411.1  542.50  5419.8  543.64
#Mann=3,-1,0
  4671.1    0.12       0  4990.0   0.046       0  5010.0    0.12       0
#XS Ineff=2,0
    0.00 4946.40  532.91 5053.60    0.00  532.91
Bank Sta=4990,5010
XS Rating Curve= 0
Exp/Cntr=0.5,0.3

Type RM Length L Ch R = 1,11852,500,500,500
BEGIN DESCRIPTION:
Mud Creek 24.0
END DESCRIPTION:
XS GIS Cut Line= 3
      1863267.90      1154121.77      1863097.56      1154177.04
      1862803.62      1154257.82
#Sta/Elev= 30
  4820.9  548.28  4835.5  542.71  4873.2  525.76  4892.2  518.51  4893.6  518.06
  4915.6  516.43  4938.6  515.02  4953.8  515.50  4957.8  515.74  4968.2  514.41
  4997.2  512.98  4998.2  510.98  5001.8  510.98  5002.8  512.98  5023.1  513.49
  5039.8  514.82  5044.8  515.37  5062.6  516.83  5121.6  526.44  5155.3  539.50
  5157.2  539.74  5175.5  541.63  5185.1  542.22  5187.2  542.52  5191.7  542.41
  5205.7  542.53  5245.8  544.93  5249.8  545.51  5286.1  547.87  5304.8  548.88
#Mann=3,-1,0
  4820.9    0.12       0  4997.2   0.046       0  5002.8    0.12       0
Bank Sta=4997.2,5002.8
XS Rating Curve= 0
Exp/Cntr=0.3,0.1

Type RM Length L Ch R = 1,11352,540,540,540
BEGIN DESCRIPTION:
Mud Creek 23.0
END DESCRIPTION:
XS GIS Cut Line= 3
      1863203.12      1153696.36      1863045.79      1153693.01
      1862678.37      1153830.25
#Sta/Elev= 30
  4842.6  542.08  4860.2  537.77  4865.0  535.80  4869.9  534.54  4902.1  522.74
  4906.9  520.82  4932.8  513.53  4934.0  513.28  4969.3  511.64  4997.2  509.07
  4998.2  507.07  5001.8  507.07  5002.8  509.07  5004.1  509.08  5018.3  510.73
  5040.3  511.47  5096.8  512.50  5122.9  512.76  5148.2  514.39  5166.4  516.00
  5196.0  520.44  5228.8  524.94  5248.2  527.84  5268.5  529.50  5298.5  532.64
  5323.5  536.85  5338.2  537.62  5365.7  540.51  5380.9  542.67  5392.2  543.18
#Mann=3,-1,0
  4842.6    0.12       0  4997.2   0.046       0  5002.8    0.12       0
Bank Sta=4997.2,5002.8
XS Rating Curve= 0
Exp/Cntr=0.3,0.1

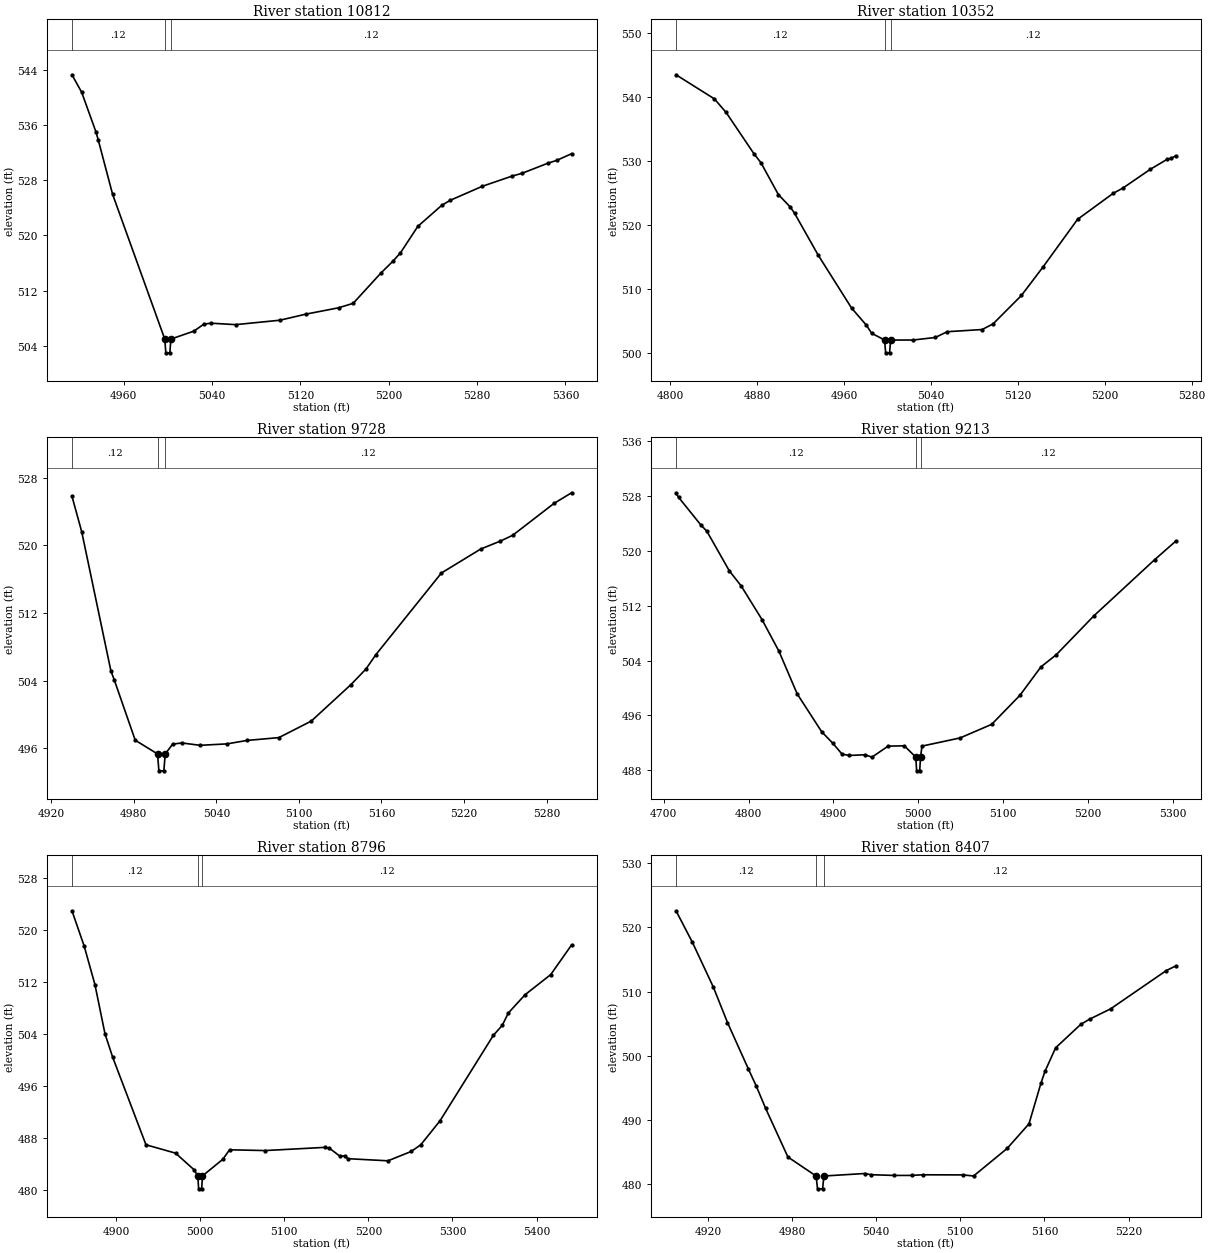
Type RM Length L Ch R = 1,10812,460,460,460
BEGIN DESCRIPTION:
Mud Creek 22.0
END DESCRIPTION:
XS GIS Cut Line= 3
      1862909.43      1153137.06      1862879.20      1153206.16
      1862591.99      1153450.18
#Sta/Elev= 29
  4913.2  543.31  4922.0  540.77  4934.9  535.03  4936.9  533.92  4950.0  525.97
  4997.2  504.98  4998.2  502.98  5001.8  502.98  5002.8  504.98  5023.6  506.13
  5032.5  507.13  5038.9  507.28  5061.4  507.07  5101.4  507.71  5124.9  508.59
  5154.5  509.51  5167.8  510.16  5192.7  514.52  5203.7  516.26  5210.5  517.46
  5226.3  521.32  5248.0  524.38  5255.6  525.10  5284.6  527.13  5311.9  528.63
  5320.5  529.01  5344.5  530.51  5352.0  530.89  5365.5  531.86
#Mann=3,-1,0
  4913.2    0.12       0  4997.2   0.046       0  5002.8    0.12       0
Bank Sta=4997.2,5002.8
XS Rating Curve= 0
Exp/Cntr=0.3,0.1

Type RM Length L Ch R = 1,10352,624,624,624
BEGIN DESCRIPTION:
Mud Creek 21.0
END DESCRIPTION:
XS GIS Cut Line= 3
      1862725.00      1152925.00      1862533.63      1152961.27
      1862325.00      1153125.00
#Sta/Elev= 30
  4805.2  543.43  4840.5  539.67  4851.3  537.55  4876.9  531.11  4883.4  529.69
  4899.4  524.73  4910.4  522.77  4914.3  521.81  4936.2  515.23  4966.8  507.00
  4980.4  504.33  4985.3  503.06  4997.2  502.00  4998.2  500.00  5001.8  500.00
  5002.8  502.00  5023.4  502.00  5043.9  502.40  5054.9  503.30  5087.0  503.64
  5097.1  504.52  5123.2  508.96  5143.1  513.41  5174.9  520.85  5207.6  524.90
  5216.6  525.73  5242.0  528.68  5257.5  530.24  5261.3  530.39  5265.2  530.78
#Mann=3,-1,0
  4805.2    0.12       0  4997.2   0.046       0  5002.8    0.12       0
Bank Sta=4997.2,5002.8
XS Rating Curve= 0
Exp/Cntr=0.3,0.1

Type RM Length L Ch R = 1,9728,515,515,515
BEGIN DESCRIPTION:
Mud Creek 20.0
END DESCRIPTION:
XS GIS Cut Line= 3
      1862170.89      1152493.54      1862157.94      1152547.53
      1862025.00      1152825.00
#Sta/Elev= 25
  4935.0  525.81  4942.1  521.60  4963.3  505.15  4965.9  504.01  4981.0  496.94
  4997.2  495.32  4998.2  493.32  5001.8  493.32  5002.8  495.32  5008.2  496.48
  5014.9  496.62  5028.1  496.34  5047.7  496.51  5062.4  496.92  5085.4  497.25
  5109.0  499.21  5137.8  503.52  5148.8  505.38  5155.8  507.04  5203.6  516.73
  5232.1  519.56  5246.5  520.51  5255.4  521.19  5285.5  524.97  5298.2  526.22
#Mann=3,-1,0
  4935.0    0.12       0  4997.2   0.046       0  5002.8    0.12       0
Bank Sta=4997.2,5002.8
XS Rating Curve= 0
Exp/Cntr=0.3,0.1

Type RM Length L Ch R = 1,9213,417,417,417
BEGIN DESCRIPTION:
Mud Creek 19.0
END DESCRIPTION:
XS GIS Cut Line= 4
      1861846.97      1152145.86      1861739.00      1152299.19
      1861695.81      1152411.48      1861633.19      1152685.73
#Sta/Elev= 30
  4714.5  528.43  4717.5  527.77  4743.4  523.80  4750.9  522.82  4777.3  517.07
  4791.3  514.87  4815.9  509.96  4835.9  505.35  4857.3  499.16  4886.3  493.62
  4899.2  491.98  4910.3  490.37  4918.9  490.18  4937.0  490.28  4945.6  489.94
  4964.6  491.54  4983.7  491.58  4997.2  489.94  4998.2  487.94  5001.8  487.94
  5002.8  489.94  5004.5  491.54  5049.4  492.73  5086.7  494.71  5120.0  498.94
  5144.8  503.08  5162.8  504.84  5207.2  510.51  5278.7  518.67  5303.6  521.37
#Mann=3,-1,0
  4714.5    0.12       0  4997.2   0.046       0  5002.8    0.12       0
Bank Sta=4997.2,5002.8
XS Rating Curve= 0
Exp/Cntr=0.3,0.1

Type RM Length L Ch R = 1,8796,389,389,389
BEGIN DESCRIPTION:
Mud Creek 18.0
END DESCRIPTION:
XS GIS Cut Line= 3
      1861464.75      1151970.95      1861412.92      1152111.31
      1861056.61      1152376.93
#Sta/Elev= 30
  4847.6  522.98  4862.2  517.51  4874.9  511.61  4886.9  504.00  4896.0  500.41
  4935.6  486.91  4970.8  485.62  4992.5  483.09  4997.2  482.12  4998.2  480.12
  5001.8  480.12  5002.8  482.12  5026.9  484.67  5035.0  486.14  5077.1  486.02
  5148.1  486.51  5153.6  486.39  5165.8  485.19  5172.3  485.19  5175.5  484.77
  5223.3  484.44  5250.9  485.88  5262.3  486.91  5285.1  490.59  5348.6  503.78
  5359.2  505.32  5366.4  507.22  5386.4  510.05  5416.8  513.14  5441.6  517.71
#Mann=3,-1,0
  4847.6    0.12       0  4997.2   0.046       0  5002.8    0.12       0
Bank Sta=4997.2,5002.8
XS Rating Curve= 0
Exp/Cntr=0.3,0.1

Type RM Length L Ch R = 1,8407,495,495,495
BEGIN DESCRIPTION:
Mud Creek 17.0
END DESCRIPTION:
XS GIS Cut Line= 3
      1861067.41      1151925.60      1861057.41      1151987.86
      1860929.20      1152251.68
#Sta/Elev= 29
  4897.3  522.60  4909.0  517.67  4923.9  510.71  4934.0  505.18  4948.9  497.94
  4954.5  495.29  4961.2  491.80  4977.1  484.22  4997.2  481.26  4998.2  479.26
  5001.8  479.26  5002.8  481.26  5031.9  481.65  5036.5  481.46  5052.9  481.35
  5065.3  481.35  5073.1  481.45  5102.1  481.43  5109.5  481.26  5133.4  485.55
  5149.0  489.39  5157.5  495.69  5160.4  497.56  5168.0  501.24  5185.9  504.89
  5192.2  505.70  5207.2  507.31  5247.0  513.29  5253.6  513.99
#Mann=3,-1,0
  4897.3    0.12       0  4997.2   0.046       0  5002.8    0.12       0
Bank Sta=4997.2,5002.8
XS Rating Curve= 0
Exp/Cntr=0.3,0.1

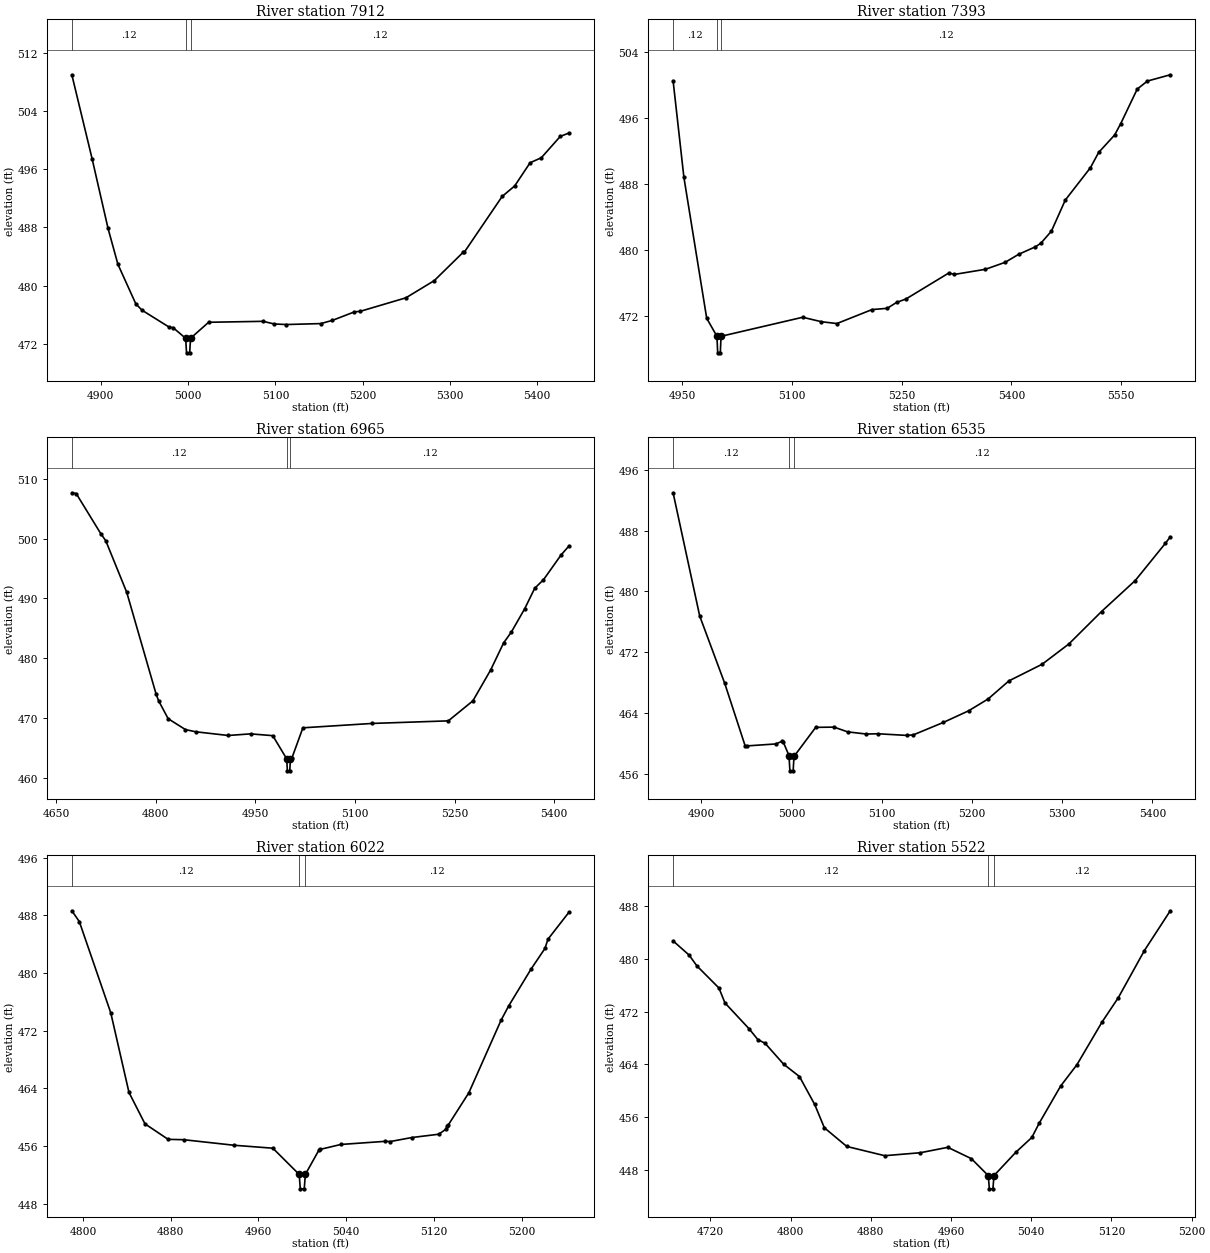
Type RM Length L Ch R = 1,7912,519,519,519
BEGIN DESCRIPTION:
Mud Creek 16.0
END DESCRIPTION:
XS GIS Cut Line= 3
      1860894.65      1151638.39      1860731.07      1151660.45
      1860425.00      1151925.00
#Sta/Elev= 30
  4866.8  508.98  4890.1  497.40  4908.3  487.86  4919.6  482.93  4940.1  477.50
  4947.2  476.63  4978.6  474.28  4982.6  474.25  4997.2  472.77  4998.2  470.77
  5001.8  470.77  5002.8  472.77  5023.5  474.97  5085.9  475.10  5098.5  474.74
  5112.3  474.66  5152.0  474.79  5165.3  475.23  5190.6  476.40  5197.4  476.48
  5249.5  478.33  5282.0  480.69  5314.9  484.56  5316.6  484.63  5359.8  492.26
  5374.2  493.71  5391.8  496.89  5404.7  497.58  5426.4  500.51  5436.4  500.98
#Mann=3,-1,0
  4866.8    0.12       0  4997.2   0.046       0  5002.8    0.12       0
Bank Sta=4997.2,5002.8
XS Rating Curve= 0
Exp/Cntr=0.3,0.1

Type RM Length L Ch R = 1,7393,428,428,428
BEGIN DESCRIPTION:
Mud Creek 15.0
END DESCRIPTION:
XS GIS Cut Line= 3
      1860499.47      1151251.85      1860421.73      1151316.63
      1860404.45      1151895.37
#Sta/Elev= 30
  4937.2  500.49  4952.0  488.80  4983.2  471.77  4997.2  469.60  4998.2  467.60
  5001.8  467.60  5002.8  469.60  5114.5  471.90  5140.2  471.36  5161.3  471.14
  5209.4  472.83  5230.1  472.98  5242.9  473.69  5255.8  474.11  5314.4  477.25
  5322.2  477.08  5364.6  477.70  5391.5  478.54  5410.0  479.51  5433.0  480.42
  5440.4  480.85  5454.8  482.31  5473.8  486.07  5508.2  489.98  5519.4  491.82
  5541.3  493.93  5549.7  495.32  5572.2  499.48  5586.1  500.45  5617.4  501.21
#Mann=3,-1,0
  4937.2    0.12       0  4997.2   0.046       0  5002.8    0.12       0
Bank Sta=4997.2,5002.8
XS Rating Curve= 0
Exp/Cntr=0.3,0.1

Type RM Length L Ch R = 1,6965,430,430,430
BEGIN DESCRIPTION:
Mud Creek 14.0
END DESCRIPTION:
XS GIS Cut Line= 4
      1860359.49      1151078.21      1860189.49      1151156.36
      1860120.94      1151275.63      1859966.08      1151670.78
#Sta/Elev= 30
  4673.5  507.64  4680.1  507.51  4717.2  500.80  4724.6  499.64  4756.2  491.03
  4800.2  474.14  4804.1  472.96  4818.6  469.94  4844.7  468.12  4860.6  467.75
  4909.2  467.14  4942.7  467.41  4976.2  467.11  4997.2  463.24  4998.2  461.24
  5001.8  461.24  5002.8  463.24  5005.0  463.37  5021.6  468.42  5126.0  469.15
  5240.7  469.58  5277.7  472.92  5304.5  478.08  5324.0  482.59  5335.7  484.41
  5355.7  488.28  5370.9  491.72  5384.0  493.12  5410.6  497.27  5422.5  498.77
#Mann=3,-1,0
  4673.5    0.12       0  4997.2   0.046       0  5002.8    0.12       0
Bank Sta=4997.2,5002.8
XS Rating Curve= 0
Exp/Cntr=0.3,0.1

Type RM Length L Ch R = 1,6535,513,513,513
BEGIN DESCRIPTION:
Mud Creek 13.0
END DESCRIPTION:
XS GIS Cut Line= 4
      1859732.86      1150992.71      1859737.18      1151113.64
      1859709.10      1151174.11      1859663.76      1151534.74
#Sta/Elev= 30
  4868.7  492.96  4898.2  476.78  4926.0  467.92  4948.5  459.76  4950.1  459.72
  4982.4  459.98  4989.8  460.34  4990.6  460.30  4997.2  458.45  4998.2  456.45
  5001.8  456.45  5002.8  458.45  5003.5  458.46  5026.8  462.16  5047.2  462.19
  5062.1  461.57  5083.0  461.28  5095.5  461.32  5128.1  461.10  5135.2  461.18
  5168.4  462.81  5196.3  464.33  5218.0  465.89  5241.0  468.26  5277.9  470.45
  5307.5  473.11  5343.7  477.37  5381.1  481.44  5414.6  486.34  5419.9  487.18
#Mann=3,-1,0
  4868.7    0.12       0  4997.2   0.046       0  5002.8    0.12       0
Bank Sta=4997.2,5002.8
XS Rating Curve= 0
Exp/Cntr=0.3,0.1

Type RM Length L Ch R = 1,6022,500,500,500
BEGIN DESCRIPTION:
Mud Creek 12.0
END DESCRIPTION:
XS GIS Cut Line= 3
      1859549.30      1150759.49      1859361.62      1150886.28
      1859164.92      1150999.19
#Sta/Elev= 30
  4789.9  488.65  4796.7  487.16  4825.4  474.48  4842.0  463.43  4856.6  459.07
  4877.7  456.92  4891.9  456.87  4937.8  456.10  4973.2  455.69  4997.2  452.05
  4998.2  450.05  5001.8  450.05  5002.8  452.05  5015.0  455.38  5016.4  455.53
  5035.2  456.21  5075.2  456.64  5080.4  456.62  5099.8  457.17  5124.4  457.63
  5131.0  458.33  5132.2  458.78  5132.9  458.86  5151.9  463.39  5181.2  473.44
  5188.2  475.44  5208.4  480.51  5221.3  483.43  5224.0  484.70  5243.2  488.46
#Mann=3,-1,0
  4789.9    0.12       0  4997.2   0.046       0  5002.8    0.12       0
Bank Sta=4997.2,5002.8
XS Rating Curve= 0
Exp/Cntr=0.3,0.1

Type RM Length L Ch R = 1,5522,579,579,579
BEGIN DESCRIPTION:
Mud Creek 11.0
END DESCRIPTION:
XS GIS Cut Line= 3
      1859337.68      1150491.72      1859029.24      1150520.87
      1858903.62      1150657.99
#Sta/Elev= 30
  4682.9  482.73  4698.9  480.57  4706.6  478.94  4728.6  475.58  4734.6  473.32
  4758.8  469.37  4767.4  467.75  4774.6  467.19  4793.1  464.02  4808.9  462.14
  4824.1  457.90  4833.7  454.37  4856.1  451.53  4893.9  450.13  4929.4  450.58
  4956.8  451.40  4980.3  449.68  4997.2  447.10  4998.2  445.10  5001.8  445.10
  5002.8  447.10  5024.8  450.68  5040.6  452.90  5047.8  455.03  5069.3  460.70
  5085.6  463.95  5110.6  470.42  5126.8  474.11  5152.8  481.26  5178.6  487.30
#Mann=3,-1,0
  4682.9    0.12       0  4997.2   0.046       0  5002.8    0.12       0
Bank Sta=4997.2,5002.8
XS Rating Curve= 0
Exp/Cntr=0.3,0.1

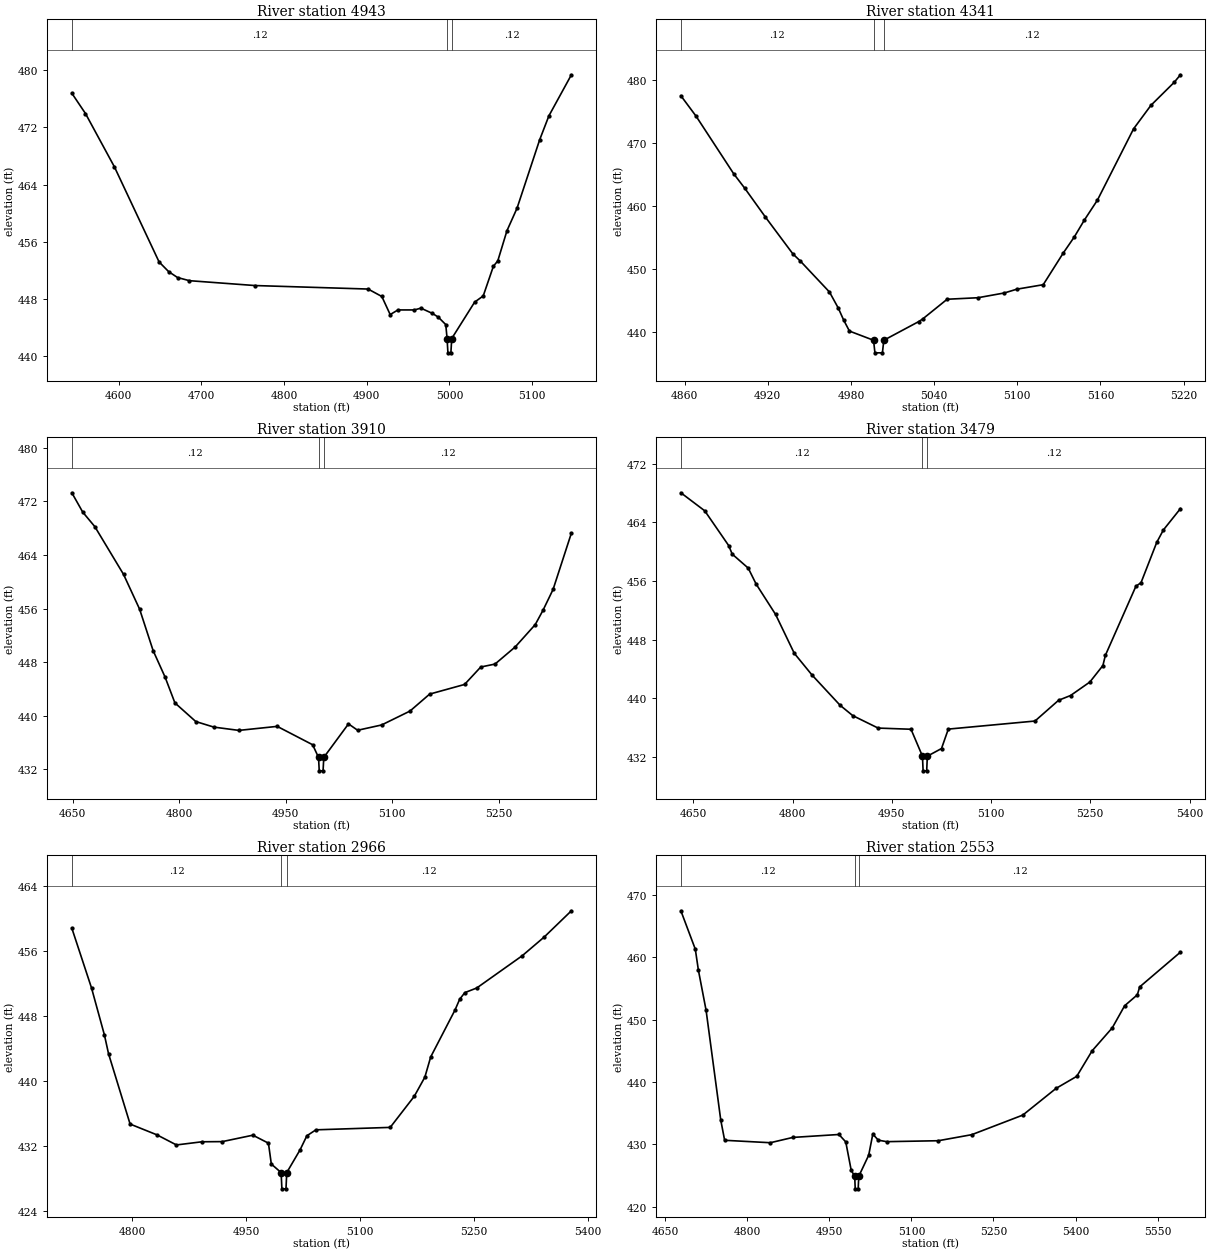
Type RM Length L Ch R = 1,4943,602,602,602
BEGIN DESCRIPTION:
Mud Creek 10.0
END DESCRIPTION:
XS GIS Cut Line= 3
      1859331.20      1150198.03      1858931.70      1149986.40
      1858780.53      1149971.28
#Sta/Elev= 30
  4543.5  476.79  4560.0  473.95  4595.0  466.49  4649.0  453.20  4660.6  451.84
  4671.3  451.02  4685.6  450.58  4764.8  449.90  4901.7  449.41  4918.3  448.37
  4928.4  445.84  4937.8  446.49  4957.7  446.49  4965.5  446.74  4979.5  446.00
  4986.5  445.49  4995.6  444.44  4997.2  442.49  4998.2  440.49  5001.8  440.49
  5002.8  442.49  5030.5  447.58  5040.9  448.45  5053.2  452.60  5058.5  453.35
  5069.6  457.57  5081.8  460.72  5109.1  470.27  5120.3  473.63  5147.5  479.37
#Mann=3,-1,0
  4543.5    0.12       0  4997.2   0.046       0  5002.8    0.12       0
Bank Sta=4997.2,5002.8
XS Rating Curve= 0
Exp/Cntr=0.3,0.1

Type RM Length L Ch R = 1,4341,431,431,431
BEGIN DESCRIPTION:
Mud Creek 9.0
END DESCRIPTION:
XS GIS Cut Line= 3
      1859063.42      1149552.35      1858944.65      1149578.26
      1858709.27      1149537.23
#Sta/Elev= 30
  4857.3  477.48  4868.3  474.22  4895.4  465.08  4903.5  462.74  4918.3  458.19
  4938.1  452.34  4943.4  451.22  4964.5  446.28  4970.9  443.71  4974.7  441.84
  4978.9  440.07  4996.3  438.61  4997.3  436.61  5002.7  436.61  5003.7  438.61
  5029.0  441.59  5031.9  442.02  5049.4  445.13  5071.6  445.37  5090.7  446.13
  5099.7  446.73  5118.7  447.44  5133.2  452.49  5141.1  455.02  5148.4  457.72
  5157.8  460.88  5183.9  472.22  5196.4  475.95  5213.2  479.61  5217.7  480.81
#Mann=3,-1,0
  4857.3    0.12       0  4996.3   0.046       0  5003.7    0.12       0
Bank Sta=4996.3,5003.7
XS Rating Curve= 0
Exp/Cntr=0.3,0.1

Type RM Length L Ch R = 1,3910,431,431,431
BEGIN DESCRIPTION:
Mud Creek 8.0
END DESCRIPTION:
XS GIS Cut Line= 3
      1859255.62      1149232.75      1858927.76      1149146.12
      1858614.26      1149332.08
#Sta/Elev= 30
  4648.8  473.26  4664.2  470.37  4681.2  468.21  4721.6  461.10  4744.3  455.90
  4763.3  449.73  4780.1  445.79  4794.0  441.93  4823.4  439.15  4848.9  438.32
  4884.1  437.83  4938.1  438.43  4988.0  435.69  4996.3  433.80  4997.3  431.80
  5002.7  431.80  5003.7  433.80  5038.5  438.80  5051.4  437.85  5085.2  438.64
  5125.1  440.71  5152.8  443.24  5202.0  444.68  5224.8  447.28  5244.9  447.72
  5273.4  450.28  5301.6  453.61  5312.5  455.74  5326.7  458.85  5352.5  467.25
#Mann=3,-1,0
  4648.8    0.12       0  4996.3   0.046       0  5003.7    0.12       0
Bank Sta=4996.3,5003.7
XS Rating Curve= 0
Exp/Cntr=0.3,0.1

Type RM Length L Ch R = 1,3479,513,513,513
BEGIN DESCRIPTION:
Mud Creek 7.0
END DESCRIPTION:
XS GIS Cut Line= 3
      1859382.41      1148804.60      1859014.82      1148776.14
      1858628.53      1148789.15
#Sta/Elev= 30
  4631.1  468.02  4667.2  465.56  4703.4  460.82  4708.7  459.66  4732.9  457.75
  4744.9  455.57  4774.3  451.43  4802.5  446.14  4829.4  443.17  4871.8  439.05
  4890.9  437.64  4929.3  435.94  4979.0  435.78  4996.3  432.11  4997.3  430.11
  5002.7  430.11  5003.7  432.11  5025.1  433.15  5035.4  435.80  5166.4  436.90
  5202.1  439.73  5220.2  440.38  5249.4  442.22  5269.1  444.47  5272.8  445.85
  5319.0  455.28  5326.7  455.76  5350.5  461.26  5360.5  462.95  5386.3  465.86
#Mann=3,-1,0
  4631.1    0.12       0  4996.3   0.046       0  5003.7    0.12       0
Bank Sta=4996.3,5003.7
XS Rating Curve= 0
Exp/Cntr=0.3,0.1

Type RM Length L Ch R = 1,2966,413,413,413
BEGIN DESCRIPTION:
Mud Creek 6.0
END DESCRIPTION:
XS GIS Cut Line= 3
      1859195.15      1148248.03      1858968.41      1148282.58
      1858648.81      1148567.63
#Sta/Elev= 30
  4720.8  458.81  4746.7  451.46  4763.7  445.67  4769.1  443.37  4797.5  434.71
  4832.9  433.38  4858.5  432.14  4892.1  432.53  4918.8  432.55  4959.1  433.34
  4979.6  432.36  4983.4  429.79  4996.3  428.74  4997.3  426.74  5002.7  426.74
  5003.7  428.74  5021.2  431.53  5030.2  433.27  5042.1  434.00  5139.9  434.30
  5171.6  438.13  5185.5  440.48  5193.2  442.97  5225.3  448.76  5231.3  450.06
  5238.1  450.88  5253.8  451.45  5313.7  455.42  5342.6  457.72  5378.4  460.95
#Mann=3,-1,0
  4720.8    0.12       0  4996.3   0.046       0  5003.7    0.12       0
Bank Sta=4996.3,5003.7
XS Rating Curve= 0
Exp/Cntr=0.3,0.1

Type RM Length L Ch R = 1,2553,369,369,369
BEGIN DESCRIPTION:
Mud Creek 5.0
END DESCRIPTION:
XS GIS Cut Line= 5
      1859136.85      1147818.30      1858887.88      1147955.27
      1858812.93      1147971.62      1858791.33      1148016.97
      1858593.43      1148478.30
#Sta/Elev= 30
  4678.6  467.45  4705.0  461.29  4710.6  457.95  4724.7  451.50  4751.5  433.91
  4758.6  430.67  4842.1  430.28  4883.3  431.13  4967.5  431.60  4980.0  430.41
  4989.9  425.88  4996.3  424.89  4997.3  422.89  5002.7  422.89  5003.7  424.89
  5021.9  428.28  5029.4  431.66  5039.5  430.69  5054.8  430.45  5149.1  430.60
  5210.3  431.57  5303.6  434.71  5364.4  438.99  5402.2  440.92  5430.2  445.00
  5467.1  448.69  5489.7  452.23  5512.9  453.98  5517.2  455.25  5591.7  460.82
#Mann=3,-1,0
  4678.6    0.12       0  4996.3   0.046       0  5003.7    0.12       0
Bank Sta=4996.3,5003.7
XS Rating Curve= 0
Exp/Cntr=0.5,0.3

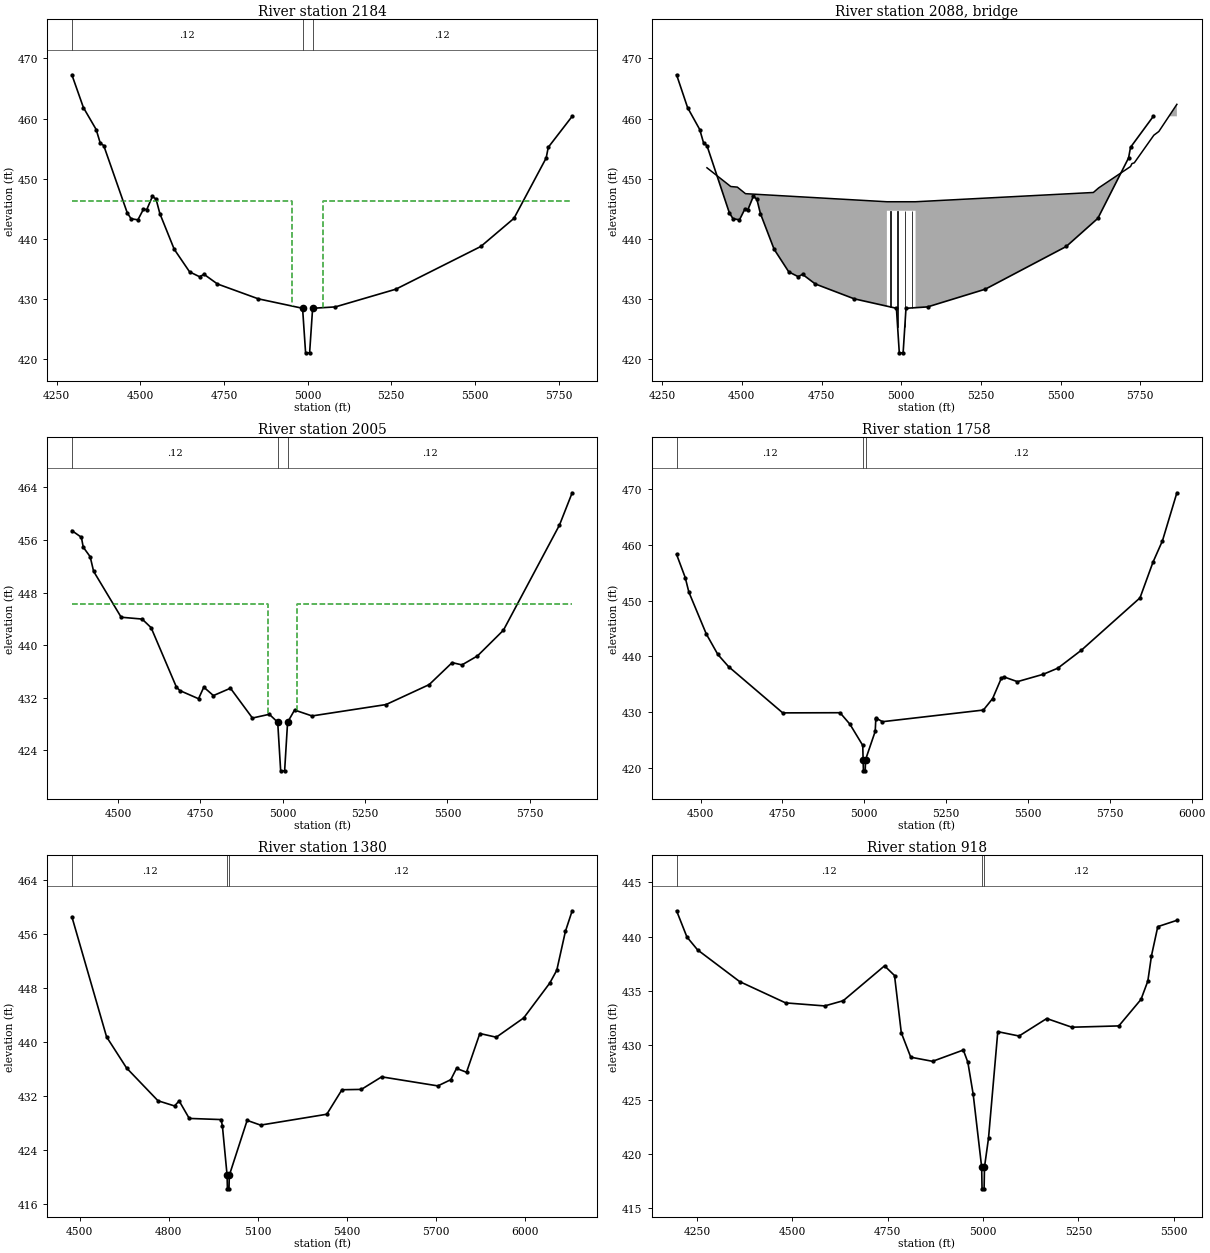
Type RM Length L Ch R = 1,2184,179,179,179
BEGIN DESCRIPTION:
Mud Creek 4.6
END DESCRIPTION:
XS GIS Cut Line= 4
      1858841.00      1146997.70      1858694.16      1147896.04
      1858625.05      1148384.08      1858592.66      1148470.46
#Sta/Elev= 30
  4295.4  467.29  4330.0  461.83  4368.0  458.20  4380.4  455.91  4390.6  455.54
  4460.9  444.36  4472.3  443.38  4492.7  443.19  4509.4  444.96  4519.3  444.90
  4536.1  447.08  4547.1  446.63  4558.4  444.23  4601.3  438.31  4647.3  434.55
  4676.9  433.75  4690.5  434.14  4730.5  432.54  4852.7  430.07  4985.0  428.50
  4994.0  421.10  5006.0  421.10  5015.0  428.50  5082.8  428.73  5263.6  431.67
  5517.8  438.77  5616.8  443.44  5713.1  453.47  5719.3  455.24  5790.8  460.39
#Mann=3,-1,0
  4295.4    0.12       0  4985.0   0.046       0  5015.0    0.12       0
#XS Ineff=2,0
    0.00 4953.50  446.32 5046.50    0.00  446.32
Bank Sta=4985,5015
XS Rating Curve= 0
Exp/Cntr=0.5,0.3

Type RM Length L Ch R =3,2088,,,
Node Photo=N:\SC_flood\60433\Survey\LDS\all_photos\LDS_MUD_CRK-01.jpg
BEGIN DESCRIPTION:
Mud Creek 4.5
Structure ID: LDS_MUD_CRK_01
Approximate Survey Structure
END DESCRIPTION:
Bridge Culvert--1,0,-1,-1,0
Deck Dist Width WeirC Skew NumUp NumDn MinLoCord MaxHiCord MaxSubmerge Is_Ogee
83,26,3,,16,16,,,,0,1,1,,,
  4390.7  4465.3  4486.0  4511.5  4955.0  4955.0  5045.0  5045.0  5602.7  5619.6
  5719.3  5723.7  5731.2  5792.4  5808.1  5864.7
  451.84  448.73  448.63  447.54  446.20  446.20  446.20  446.20  447.74  448.51
  452.05  452.53  452.67  457.25  457.87  462.38
  401.10  401.10  401.10  401.10  401.10  444.70  444.70  401.10  401.10  401.10
  401.10  401.10  401.10  401.10  401.10  401.10
  4390.7  4465.3  4486.0  4511.5  4955.0  4955.0  5045.0  5045.0  5602.7  5619.6
  5719.3  5723.7  5731.2  5792.4  5808.1  5864.7
  451.84  448.73  448.63  447.54  446.20  446.20  446.20  446.20  447.74  448.51
  452.05  452.53  452.67  457.25  457.87  462.38
  401.10  401.10  401.10  401.10  401.10  444.70  444.70  401.10  401.10  401.10
  401.10  401.10  401.10  401.10  401.10  401.10
Pier Skew, UpSta & Num, DnSta & Num=,4966.3,2,4966.3,2,0,0,0,0,0
       1       1
  423.76  444.70
       1       1
  429.04  444.70
Pier Skew, UpSta & Num, DnSta & Num=,4988.8,2,4988.8,2,0,0,0,0,0
       1       1
  425.38  444.70
       1       1
  425.13  444.70
Pier Skew, UpSta & Num, DnSta & Num=,5011.3,2,5011.3,2,0,0,0,0,0
       1       1
  425.46  444.70
       1       1
  425.21  444.70
Pier Skew, UpSta & Num, DnSta & Num=,5033.8,2,5033.8,2,0,0,0,0,0
       1       1
  424.19  444.70
       1       1
  430.04  444.70
BR Coef=1,1,0,1.25,0,,,0.8,0,2,0,
WSPro=,,,, 1 ,,,, 0 ,,,, 0 ,,,,-1 ,-1 ,-1 , 0 , 0 , 0 , 0 , 0
BC Design=,,0,,0,,,,,,

Type RM Length L Ch R = 1,2005,247,247,247
BEGIN DESCRIPTION:
Mud Creek 4.4
END DESCRIPTION:
XS GIS Cut Line= 3
      1858745.98      1146939.40      1858644.49      1147386.41
      1858495.48      1148435.91
#Sta/Elev= 30
  4360.3  457.43  4389.2  456.41  4394.8  454.91  4415.8  453.46  4426.3  451.23
  4509.9  444.24  4573.5  443.96  4600.8  442.65  4677.5  433.61  4688.1  433.07
  4744.7  431.83  4760.7  433.59  4789.9  432.31  4841.6  433.43  4908.3  428.89
  4959.6  429.46  4985.0  428.25  4994.0  420.85  5006.0  420.85  5015.0  428.25
  5036.2  430.11  5089.2  429.21  5313.7  430.94  5444.7  433.98  5514.5  437.33
  5544.2  436.98  5591.3  438.35  5670.0  442.26  5840.2  458.28  5878.7  463.19
#Mann=3,-1,0
  4360.3    0.12       0  4985.0   0.046       0  5015.0    0.12       0
#XS Ineff=2,0
    0.00 4955.20  446.20 5044.80    0.00  446.20
Bank Sta=4985,5015
XS Rating Curve= 0
Exp/Cntr=0.5,0.3

Type RM Length L Ch R = 1,1758,378,378,378
BEGIN DESCRIPTION:
Mud Creek 4.0
END DESCRIPTION:
XS GIS Cut Line= 3
      1858720.37      1146925.40      1858469.20      1147354.81
      1858226.14      1148356.77
#Sta/Elev= 30
  4426.4  458.29  4452.9  454.13  4463.9  451.54  4517.1  444.04  4552.5  440.35
  4585.1  438.18  4750.7  429.88  4925.8  429.91  4956.1  427.84  4995.2  424.05
  4996.3  421.49  4997.3  419.49  5002.7  419.49  5003.7  421.49  5033.3  426.58
  5035.0  428.71  5036.7  428.92  5055.4  428.30  5363.8  430.39  5392.0  432.45
  5418.3  436.06  5426.0  436.34  5467.7  435.48  5546.7  436.80  5591.3  437.90
  5663.2  441.12  5842.2  450.50  5881.9  456.90  5910.9  460.75  5954.9  469.34
#Mann=3,-1,0
  4426.4    0.12       0  4996.3   0.046       0  5003.7    0.12       0
Bank Sta=4996.3,5003.7
XS Rating Curve= 0
Exp/Cntr=0.3,0.1

Type RM Length L Ch R = 1,1380,462,462,462
BEGIN DESCRIPTION:
Mud Creek 3.0
END DESCRIPTION:
XS GIS Cut Line= 3
      1858723.07      1146887.59      1858250.49      1147120.11
      1857996.58      1148251.44
#Sta/Elev= 30
  4473.1  458.57  4590.1  440.77  4657.5  436.16  4763.3  431.31  4819.0  430.54
  4834.7  431.28  4868.7  428.69  4976.4  428.52  4980.6  427.50  4996.3  420.26
  4997.3  418.26  5002.7  418.26  5003.7  420.26  5063.8  428.40  5109.1  427.70
  5332.3  429.31  5383.4  432.94  5448.8  432.99  5517.2  434.85  5706.6  433.51
  5750.2  434.43  5769.5  436.10  5803.2  435.53  5848.1  441.27  5903.5  440.72
  5996.0  443.58  6083.8  448.74  6107.4  450.64  6136.5  456.40  6159.3  459.45
#Mann=3,-1,0
  4473.1    0.12       0  4996.3   0.046       0  5003.7    0.12       0
Bank Sta=4996.3,5003.7
XS Rating Curve= 0
Exp/Cntr=0.3,0.1

Type RM Length L Ch R = 1,918,568,568,568
BEGIN DESCRIPTION:
Mud Creek 2.0
END DESCRIPTION:
XS GIS Cut Line= 3
      1858625.00      1146625.00      1857914.62      1146977.56
      1857605.46      1147394.88
#Sta/Elev= 30
  4196.0  442.38  4223.1  439.97  4251.1  438.78  4361.5  435.86  4482.0  433.90
  4584.6  433.62  4633.1  434.10  4741.5  437.31  4767.7  436.42  4785.5  431.15
  4810.3  428.90  4867.5  428.52  4948.2  429.56  4960.1  428.43  4974.1  425.48
  4996.3  418.78  4997.3  416.78  5002.7  416.78  5003.7  418.78  5014.3  421.45
  5038.6  431.25  5094.4  430.85  5167.0  432.46  5232.8  431.66  5356.1  431.78
  5414.3  434.22  5432.2  435.91  5441.8  438.25  5458.3  440.92  5508.4  441.50
#Mann=3,-1,0
  4196.0    0.12       0  4996.3   0.046       0  5003.7    0.12       0
Bank Sta=4996.3,5003.7
XS Rating Curve= 0
Exp/Cntr=0.3,0.1

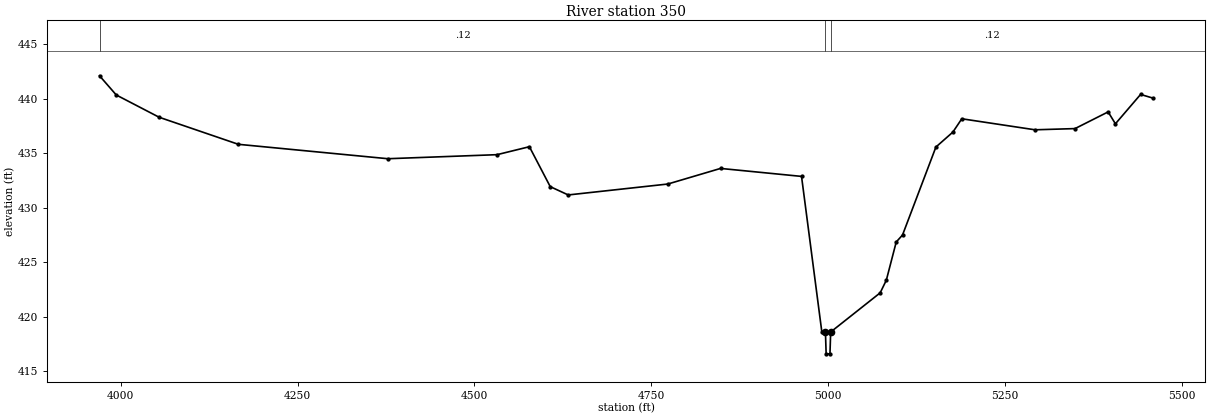
Type RM Length L Ch R = 1,350,0,0,0
BEGIN DESCRIPTION:
Mud Creek 1.0
END DESCRIPTION:
XS GIS Cut Line= 4
      1858627.21      1146585.07      1858366.01      1146604.68
      1857629.15      1146869.33      1857554.00      1147307.27
#Sta/Elev= 30
  3969.9  442.09  3993.6  440.33  4054.2  438.29  4166.2  435.81  4377.6  434.49
  4531.9  434.86  4577.7  435.59  4607.2  431.93  4632.6  431.17  4773.4  432.17
  4848.0  433.60  4962.5  432.87  4991.2  418.62  4996.3  418.61  4997.3  416.61
  5002.7  416.61  5003.7  418.61  5073.7  422.20  5082.4  423.36  5096.4  426.86
  5105.3  427.50  5152.5  435.56  5176.5  436.93  5189.1  438.15  5292.6  437.14
  5349.2  437.25  5396.0  438.78  5406.3  437.69  5441.9  440.38  5459.1  440.05
#Mann=3,-1,0
  3969.9    0.12       0  4996.3   0.046       0  5003.7    0.12       0
Bank Sta=4996.3,5003.7
XS Rating Curve= 0
Exp/Cntr=0.3,0.1

Chan Stop Cuts=-1